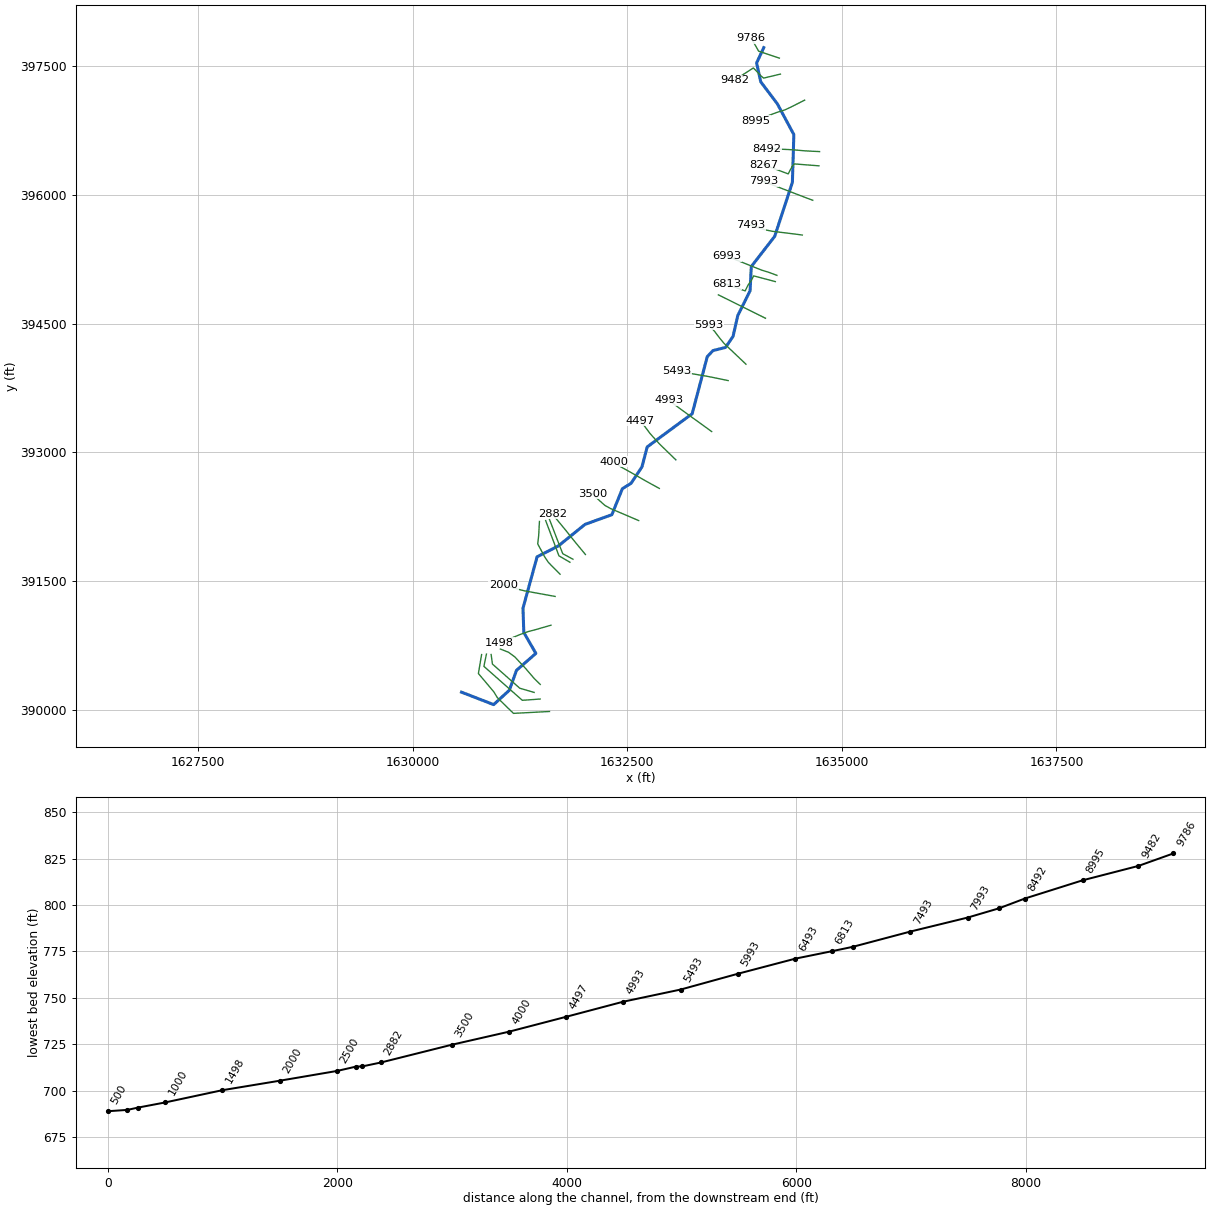
--- SHENANGOCK.prj (project) ---

Proj Title=SHENANGOCK
Current Plan=p01
Default Exp/Contr=0,0
English Units
Geom File=g01
Flow File=f01
Plan File=p01
BEGIN DESCRIPTION:
---------- MODELED AS PART OF WVEMD CTP PROGRAM, 2023----------
Stream Name: Shenango Creek
Flood Zone:  AFH
Wetzel County, WV
HEC-RAS Version: RAS 6.3
Vertical Datum: NAVD88
Projection: NAD 1983 StatePlane West Virginia S FIPS 4702 (US Feet)
Terrain: 1-meter West Virginia FEMA R3 South Central (collected 2018-2020)
Land Use: 2019 NLCD
Hydrologic Method:
WV SIR2010-5033 regression equations
Additional Model Notes:
None
END DESCRIPTION:
DSS Export Rating Curves= 0
DSS Export Rating Curve Sorted= 0
DSS Export Volume Flow Curves= 0
DXF OffsetX= 0
DXF OffsetY= 0
DXF ScaleX= 0
DXF ScaleY= 0

--- SHENANGOCK.p01 (plan) ---

Plan Title=Floodplain
Program Version=6.30
Short Identifier=Floodplain
Geom File=g01
Flow File=f01
Subcritical Flow
K Sum by GR= 0
Std Step Tol= 0.01
Critical Tol= 0.01
Num of Std Step Trials= 20
Max Error Tol= 0.3
Flow Tol Ratio= 0.001
Split Flow NTrial= 30
Split Flow Tol= 0.02
Split Flow Ratio= 0.02
Log Output Level= 0
Friction Slope Method= 1
Unsteady Friction Slope Method= 2
Unsteady Bridges Friction Slope Method= 1
Parabolic Critical Depth
Global Vel Dist= 0 , 0 , 0
Global Log Level= 0
CheckData=True
Encroach Param=-1 ,0,0, 0
Mapping Interval=1HOUR
Computation Time Step Use Courant=        0
Computation Time Step Use Time Series=    0
Computation Time Step Count To Double=0
Computation Time Step Max Doubling=0
Computation Time Step Max Halving=0
Computation Time Step Residence Courant=0
Run HTab= 0
Run UNet= 0
Run Sediment= 0
Run PostProcess= 0
Run WQNet= 0
Run RASMapper= 0
UNET Theta= 0
UNET Theta Warmup= 0
UNET ZTol= 0
UNET ZSATol= 0
UNET MxIter= 0
UNET Max Iter WO Improvement= 0
UNET MaxInSteps= 0
UNET DtIC= 0
UNET DtMin= 0
UNET MaxCRTS= 0
UNET WFStab= 0
UNET SFStab= 0
UNET WFX= 1
UNET SFX= 1
UNET Gravity=32.17405
UNET 1D Methodology=Finite Difference
UNET DSS MLevel= 1
UNET Pardiso=0
UNET DZMax Abort= 0
UNET Use Existing IB Tables= 0
UNET Froude Reduction=False
UNET Froude Limit= 0
UNET Froude Power= 0
UNET D1 Cores= 0
UNET WindReference=Eulerian
UNET WindDragFormulation=Hsu (1988)
UNET D2 Coriolis=0
UNET D2 Cores= 0
UNET D2 Theta= 1
UNET D2 Theta Warmup= 1
UNET D2 Z Tol= 0.01
UNET D2 Volume Tol= 0.01
UNET D2 Max Iterations= 20
UNET D2 Equation= 0
UNET D2 RampUpFraction=0.1
UNET D2 TimeSlices= 1
UNET D2 Turbulence Formulation=Non-Conservative (original)
UNET D2 Eddy Viscosity=0.3
UNET D2 Transverse Eddy Viscosity=0.1
UNET D2 Smagorinsky Mixing=0
UNET D2 BCVolumeCheck=0
UNET D2 Cores=0
UNET D2 SolverType=PARDISO (Direct)
UNET D2 Minimum Iterations= 3
UNET D2 Maximum Iterations= 30
UNET D2 Restart Number= 10
UNET D2 Relaxation Coeff=1.3
UNET D2 SOR Precondition Iterations= 10
UNET D2 ILUT Maximum Fill= 8
UNET D2 ILUT Tolerance=1E-08
UNET D2 Convergence Tolerance=0.00001
UNET D1D2 MaxIter= 0
UNET D1D2 ZTol=0.01
UNET D1D2 QTol=0.1
UNET D1D2 MinQTol=1
Write IC File= 0
Write IC File at Fixed DateTime=0
Write IC File at Sim End=0
Echo Input=False
Echo Parameters=False
Echo Output=False
Write Detailed= 0
HDF Write Warmup=0
HDF Write Time Slices=0
HDF Flush=0
HDF Compression= 1
HDF Chunk Size= 1
HDF Spatial Parts= 1
HDF Use Max Rows=0
HDF Fixed Rows= 1
Calibration Method= 0
Calibration Iterations= 20
Calibration Max Change=0.05
Calibration Tolerance=0.2
Calibration Maximum=1.5
Calibration Minimum=0.5
Calibration Optimization Method= 1
WQ AD Non Conservative
WQ ULTIMATE=-1
WQ Max Comp Step=1HOUR
WQ Output Interval=15MIN
WQ Output Selected Increments= 0
WQ Output face flow=0
WQ Output face velocity=0
WQ Output face area=0
WQ Output face dispersion=0
WQ Output cell volume=0
WQ Output cell surface area=0
WQ Output cell continuity=0
WQ Output cumulative cell continuity=0
WQ Output face conc=0
WQ Output face dconc_dx=0
WQ Output face courant=0
WQ Output face peclet=0
WQ Output face adv mass=0
WQ Output face disp mass=0
WQ Output cell mass=0
WQ Output cell source sink temp=0
WQ Output nsm pathways=0
WQ Output nsm derived pathways=0
WQ Create Restart=0
WQ Fixed Restart=0
WQ System Summary=0
WQ Write To DSS=0
Sorting and Armoring Iterations= 10
XS Update Threshold= 0.02
Bed Roughness Predictor= 0
Hydraulics Update Threshold= 0.02
Energy Slope Method= 1
Volume Change Method= 1
Sediment Retention Method= 0
Sediment TS Multiplier= 1
Warm Up Method= 0
XS Weighting Method= 0
Number of US Weighted Cross Sections= 1
Number of DS Weighted Cross Sections= 1
Upstream XS Weight=0
Main XS Weight=1
Downstream XS Weight=0
Number of DS XS's Weighted with US Boundary= 1
Upstream Boundary Weight= 1
Weight of XSs Associated with US Boundary= 0
Number of US XS's Weighted with DS Boundary= 1
Downstream Boundary Weight= 0.5
Weight of XSs Associated with DS Boundary= 0.5
Percentile Method= 0
Sediment Output Level= 3
Mass or Volume Output= 0
Output Increment Type= 1
Profile and TS Output Increment= 1
Transport Output Increment 1
XS Output Flag= 0
XS Output Increment= 10
Read HDF5 Sediment Hotstart= 0
Sediment Hotstart Type= 0
Write Gradation File= 0
Read Gradation Hotstart= 0
Write HDF5 File= 1
Write Binary Output= 1
Write DSS Sediment File= 0
DSS Sediment Output Type= 1
SV Curve= 0
Specific Gage Flag= 0
Subcell Erosion Methods= 0
Subcell Deposition Methods= 0
Advection Scheme= 1
Matrix Solver= 0
Implicit Weighting Factor= 1
Maximum Outer Loop Convergence Iterations= 5
Convergence Maximum Absolute= 0.001
Convergence RMSE= 0.0001
Grain Fractions Max Abs Error= 0.001
Max Subgrid Regions= 1
Max Subgrid Length Scale= 3.402823E+38
Initial Layer Thickness= 3.402823E+38
Min Layer Thickness= 3.402823E+38
Max Layer Thickness= 3.402823E+38
Number of Layers= 5

--- SHENANGOCK.f01 (steady flow) ---

Flow Title=Flow
Program Version=4.00
Number of Profiles=1
Profile Names=F01pct
River Rch & RM=SHENANGOCK,Main,9786
     618
River Rch & RM=SHENANGOCK,Main,8267
     770
River Rch & RM=SHENANGOCK,Main,5993
     997
River Rch & RM=SHENANGOCK,Main,3500
    1110
Boundary for River Rch & Prof#=SHENANGOCK,Main      ,1
Up Type=0
Dn Type=3
Dn Slope=0.013672

--- SHENANGOCK.g01 (geometry) ---

Geom Title=Geometry
Program Version=6.31

River Reach=SHENANGOCK      ,Main
Reach XY= 30
     1634091.433      397714.441     1634007.918      397536.325
     1634055.957      397316.452     1634249.224      397060.734
     1634441.752      396701.546     1634424.753      396145.396
     1634218.922      395516.448     1633945.836      395164.281
     1633932.163      394882.696     1633788.784       394593.72
     1633733.353      394350.935     1633645.843       394222.06
     1633499.438      394185.384     1633433.291      394115.172
     1633257.393      393450.009     1632733.393      393063.106
     1632672.789      392831.408     1632545.669       392639.62
     1632444.786      392576.798     1632321.362       392273.41
     1632009.474      392161.072     1631698.695      391909.788
     1631450.737      391783.038     1631286.294      391183.283
     1631296.272      390901.697     1631436.695      390657.804
     1631211.279      390461.581     1631127.394      390228.774
     1630944.955      390061.329     1630570.302      390206.347

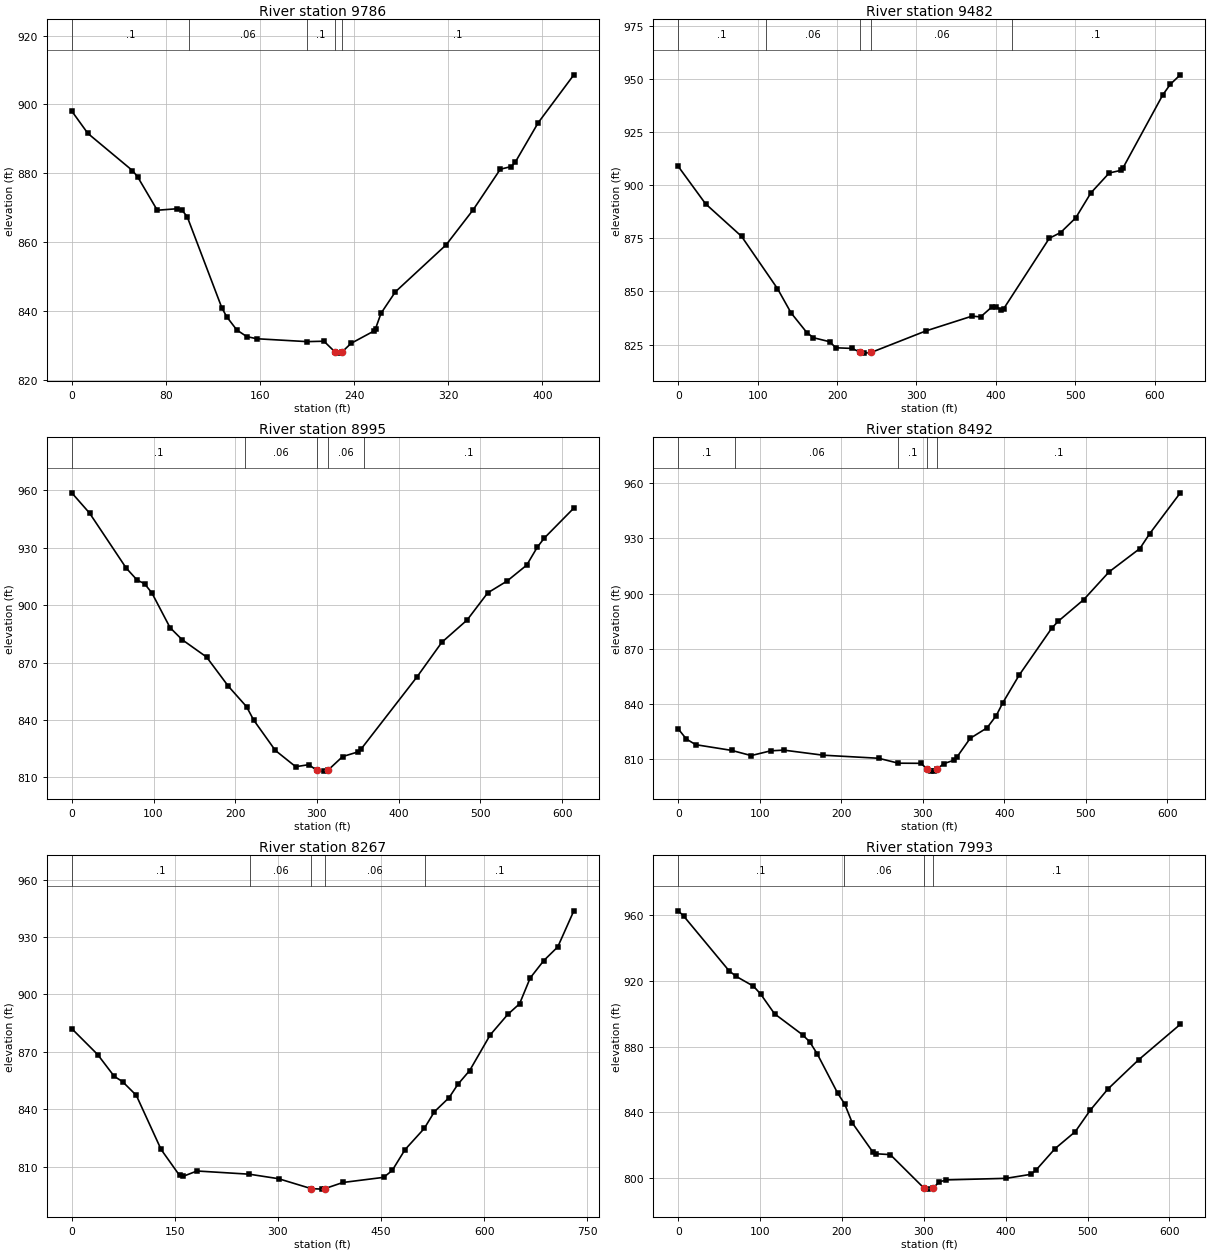
Type RM Length L Ch R = 1 ,9786    ,309.7,304.6,303
XS GIS Cut Line= 3
1634273.04949682 397592.076296381634031.62654823 397673.43983154
1633946.26152774397822.828617408
#Sta/Elev= 30
       0  898.06    13.7  891.57    51.6  880.78    55.9  879.01    72.7  869.26
    89.6   869.7    93.9  869.19    98.1  867.41   127.6   840.9   131.8  838.28
   140.3  834.49   148.7  832.57   157.2  831.94     200   831.1   214.4  831.22
   223.6  828.15   228.4  827.76  229.93  828.15   237.4  830.59   256.7  834.15
   258.3  834.91   262.9  839.33   275.1  845.56   318.2  859.19   341.3  869.42
   364.3  881.17   373.5  881.94   376.9  883.15   396.5  894.67426.8234  908.59
#Mann= 5 ,-1,0
       0      .1       0     100     .06       0     200      .1       0
   223.6    .045       0  229.93      .1       0
Bank Sta=223.6,229.93
XS Rating Curve= 0 ,0
Exp/Cntr(USF)=0,0
Exp/Cntr=0.3,0.1

Type RM Length L Ch R = 1 ,9482    ,477.4,486.9,489.3
BEGIN DESCRIPTION:
Low water crossing
END DESCRIPTION:
XS GIS Cut Line= 6
1634285.59185402 397406.422849841634090.29720226397359.602877735
1634055.64225848397387.1693102871634012.32357876397435.213664164
1633969.79251139 397477.744731531633749.49253958397335.440207258
#Sta/Elev= 30
       0  908.81    34.4  891.22    79.7  875.93   124.9  851.39   142.1  839.93
   161.9  830.71   170.2  828.27   190.7  826.39   198.5  823.54   219.1  823.24
   229.3  821.38   234.4  821.03  243.22821.3846   311.7  831.45     370  838.43
   380.7  838.05   395.2  842.83   400.5   842.9   406.8  841.28   409.7  841.84
   467.2     875   481.5  877.72   500.5  884.61   519.6  896.35   542.7  905.71
   557.2  906.93   560.1  908.14   610.1   942.4   619.6   947.4   632.2  951.85
#Mann= 5 ,-1,0
       0      .1       0     110     .06       0   229.3    .045       0
  243.22     .06       0  419.96      .1       0
Bank Sta=229.3,243.22
XS Rating Curve= 0 ,0
Exp/Cntr(USF)=0,0
Exp/Cntr=0.3,0.1

Type RM Length L Ch R = 1 ,8995    ,503.4,502.6,498.5
XS GIS Cut Line= 6
 1634567.4101951397102.7480873321634404.88394535397020.677713424
1634336.52515817396988.8483807591634241.08506034396958.842535257
1634170.73349501396932.372771919 1634002.8499725396863.151125595
#Sta/Elev= 30
       0  958.73    21.7  948.17    66.6   919.4      80  913.12      89  911.25
      98  906.42   120.3  888.24     135  881.99   164.9  872.91   191.7  857.58
   213.8  846.98   222.6  839.94     249  824.12     274  815.57     290  816.65
   299.8  813.69   308.2  813.27  313.42813.7294   331.4  820.88   350.2  823.31
   354.4  825.03   422.7   862.7   452.8  880.62   483.7  892.25   508.9  906.43
   532.7  912.65   556.6  920.93   569.6  930.33   578.2  935.11   614.3  950.76
#Mann= 5 ,-1,0
       0      .1       0  212.07     .06       0   299.8    .045       0
  313.42     .06       0  357.48      .1       0
Bank Sta=299.8,313.42
XS Rating Curve= 0 ,0
Exp/Cntr(USF)=0,0
Exp/Cntr=0.3,0.1

Type RM Length L Ch R = 1 ,8492    ,216.8,225.2,234.8
XS GIS Cut Line= 6
1634741.49088368396503.5199550841634646.76436709396507.913647085
  1634558.173665396513.3280063421634482.34934159396520.158045173
1634382.56246768396527.1225981711634126.57675917 396538.75479275
#Sta/Elev= 30
       0  826.43     9.9  820.95    21.4  817.85    65.4  814.75    89.5  811.93
   113.5  814.51   129.5  814.89   177.6  812.14   245.9  810.46     270  807.79
     298  807.71   304.8  804.75   310.1  803.47   314.1  803.58  317.78  804.76
   326.1  807.58   338.1  809.37   342.2  811.29   358.2  821.31   378.8  826.97
   390.2  833.66   398.2  840.62   418.3  855.67   458.3  881.22   466.3  884.99
   497.5  896.71   528.6   911.8   566.4   924.5   578.4  932.55     616  954.78
#Mann= 5 ,-1,0
       0      .1       0      70     .06       0  269.72      .1       0
   304.8    .045       0  317.78      .1       0
Bank Sta=304.8,317.78
XS Rating Curve= 0 ,0
Exp/Cntr(USF)=0,0
Exp/Cntr=0.3,0.1

Type RM Length L Ch R = 1 ,8267    ,282.9,273.9,260.7
BEGIN DESCRIPTION:
Low water crossing
END DESCRIPTION:
XS GIS Cut Line= 6
1634733.76022781396337.6178248351634446.10135367396360.010431804
 1634423.1345773396330.7277919221634401.89030915396293.406780308
1634376.62685513396243.4540416871634090.11631982396350.823721253
#Sta/Elev= 30
       0  882.07    37.7  868.53    61.8  857.15    73.9  854.38    93.9  847.23
     130  818.92   156.9  805.33   162.1  804.89   182.2  807.68   258.4     806
   300.9  803.65   348.4  798.46   364.3   798.2  368.51798.4937   394.5  801.67
   453.9  804.36   466.3  807.96     485  818.87   512.9   829.9   527.7  838.66
   549.1  846.03   561.9  853.01     579  860.18   608.9  878.81   634.5  889.54
   651.6  895.06   667.1  908.58   686.9  917.67   707.2  924.81   730.6  943.66
#Mann= 5 ,-1,0
       0      .1       0     260     .06       0   348.4    .045       0
  368.51     .06       0  514.68      .1       0
Bank Sta=348.4,368.51
XS Rating Curve= 0 ,0
Exp/Cntr(USF)=0,0
Exp/Cntr=0.3,0.1

Type RM Length L Ch R = 1 ,7993    ,497.2,499.6,501
XS GIS Cut Line= 6
1634662.20757768395936.4459580031634573.66608809395969.510852501
1634491.99860051396000.9225350921634421.99775626396027.845709592
1634328.66264109396063.7426194251634089.49317193396155.731608674
#Sta/Elev= 30
       0  962.69     6.5  959.59      62  926.22    70.6  922.81    91.9  916.79
   100.5  912.11   117.6     900   151.9  887.18   160.5  882.97   169.8  875.56
   194.7  851.69   203.3  845.05   212.6  833.54   237.6  815.87   241.9  814.72
     259  814.22  299.77  794.03   305.4   793.2   311.6  794.04     319  797.62
   327.6  798.82   400.5  799.77   430.5  802.19   437.2  804.88   460.2  817.82
     485  828.21   503.3  841.27   524.7  854.09   562.3  871.94   613.3  893.57
#Mann= 4 ,-1,0
       0      .1       0  202.01     .06       0  299.77    .045       0
   311.6      .1       0
Bank Sta=299.77,311.6
XS Rating Curve= 0 ,0
Exp/Cntr(USF)=0,0
Exp/Cntr=0.3,0.1

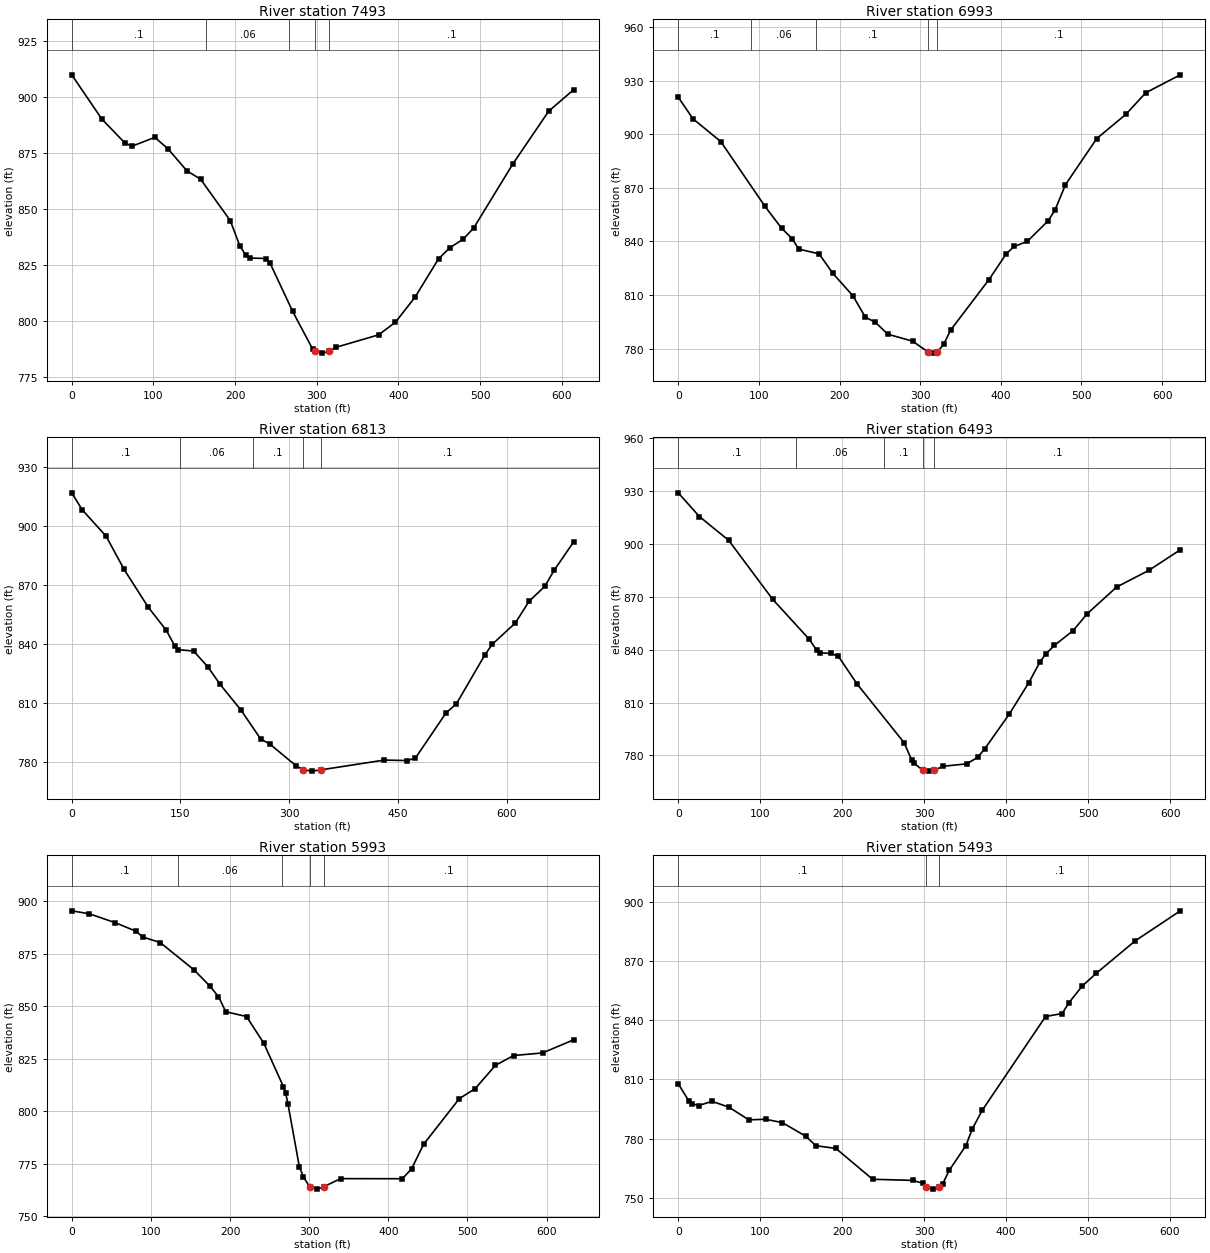
Type RM Length L Ch R = 1 ,7493    ,502.9,500.4,496.7
XS GIS Cut Line= 6
  1634540.654015395531.3614663331634447.72014576395543.779748589
1634187.14783226395575.5428084281634113.54266451395591.196648508
1634028.76100992395615.1710100021633939.09255409 395646.83466059
#Sta/Elev= 30
       0  909.95    36.9  890.15    65.1  879.49    73.8  878.08   101.6  882.01
   117.5  877.03   140.9   867.1   157.8  863.29   194.1  844.83   205.7  833.61
   212.9  829.43   218.2  828.13   238.4  827.91   242.4  826.13   270.4  804.32
   294.8  787.54  297.85  786.44   306.9  785.66     315  786.46     323  788.21
   375.7  793.83   396.2  799.43   420.4  810.72     449  827.75   462.9  832.75
   479.1  836.51   492.1  841.55     540  870.14   583.9  893.71   614.7  903.38
#Mann= 5 ,-1,0
       0      .1       0  163.76     .06       0  266.26      .1       0
  297.85    .045       0     315      .1       0
Bank Sta=297.85,315
XS Rating Curve= 0 ,0
Exp/Cntr(USF)=0,0
Exp/Cntr=0.3,0.1

Type RM Length L Ch R = 1 ,6993    ,168.4,180,191.6
XS GIS Cut Line= 6
1634245.24679743   395061.9201481634150.10984859395096.859382585
1634064.25372109  395123.70939451633994.54027784395151.372068837
1633832.21875209395216.7685915831633664.09999384 395284.50041151
#Sta/Elev= 30
       0  920.81    18.3  908.67    52.8  895.91   107.6  859.61   128.2  847.38
   141.2  841.63   149.5  835.72   174.7  833.05   191.5  822.25   216.7  809.49
   232.1  797.55   244.4  794.76   259.8  788.07   290.5  784.16  310.14  778.02
   316.4  777.46   321.3  778.04   329.3  782.55   337.9  790.45   385.4  818.67
   406.9  833.18   416.6   837.2   432.8     840   458.7  851.56   467.3  857.66
   480.2  871.79     519  897.62   554.9   911.1   579.8  923.27   622.6   933.3
#Mann= 5 ,-1,0
       0      .1       0      90     .06       0  171.35      .1       0
  310.14    .045       0   321.3      .1       0
Bank Sta=310.14,321.3
XS Rating Curve= 0 ,0
Exp/Cntr(USF)=0,0
Exp/Cntr=0.3,0.1

Type RM Length L Ch R = 1 ,6813    ,331.9,320,306.2
BEGIN DESCRIPTION:
Low water crossing
END DESCRIPTION:
XS GIS Cut Line= 6
1634225.96320149394989.1360308481633973.92724673 395055.64551891
1633943.29787723394997.0121544351633908.29288351394948.880288074
1633875.03813948394880.6205503251633658.00717843394957.631536503
#Sta/Elev= 30
       0  917.01    14.3  908.41    47.4  894.87    72.2  877.96   105.3  858.81
   130.2  847.02   142.6  838.71   146.7  837.03     168  836.37   188.1  828.15
   204.6  819.37   233.6  806.18   260.7  791.48   273.1     789   309.1  777.95
  319.56775.7833   331.6  775.12   343.7  775.77   431.5  780.77   462.5  780.51
   474.1  781.71   516.6   804.9   530.6  809.33   569.9  834.31   580.2  839.79
     612  850.62   631.2  861.81   652.7  869.31   665.6  877.53   692.8  892.13
#Mann= 5 ,-1,0
       0      .1       0     150     .06       0     250      .1       0
  319.56    .045       0   343.7      .1       0
Bank Sta=319.56,343.7
XS Rating Curve= 0 ,0
Exp/Cntr(USF)=0,0
Exp/Cntr=0.3,0.1

Type RM Length L Ch R = 1 ,6493    ,501.1,499.8,495
XS GIS Cut Line= 6
1634111.25067434394562.3027089241633948.90618275394642.899988666
1633881.72947983 394676.250643761633792.16010517394720.718074501
1633724.98307417394754.0684015011633562.63891068394834.665681258
#Sta/Elev= 30
       0   929.1    25.8  915.65    61.6  902.09   115.1  868.69   159.8  845.98
   168.7  839.84   173.2  838.23   186.6  837.91   195.5  836.21   217.9  820.73
   275.6   787.2   284.8  777.41   287.5  775.69   298.2  771.65   305.4   771.1
  312.37  771.65   323.3  773.87   351.8  775.23   365.2  778.89   374.2  783.92
   403.9  803.51   427.8   821.4   441.2  833.04   448.7  837.72     459  842.54
   481.5  850.77   499.2  860.57   534.9  875.64     574  885.04   612.5  896.76
#Mann= 5 ,-1,0
       0      .1       0  143.75     .06       0  251.25      .1       0
   298.2    .045       0  312.37      .1       0
Bank Sta=298.2,312.37
XS Rating Curve= 0 ,0
Exp/Cntr(USF)=0,0
Exp/Cntr=0.3,0.1

Type RM Length L Ch R = 1 ,5993    ,497.7,500.2,506.5
XS GIS Cut Line= 6
1633884.27409418394026.5754339251633698.43161809394202.892338499
1633626.15485975394272.0395099221633577.10836992394331.782828748
1633519.60061093394407.4893702571633450.18703584394487.325824752
#Sta/Elev= 30
       0  895.52    22.3   894.1    55.2  889.83    80.7  885.88      90  883.01
   111.8  880.41   154.3  867.45   174.1  859.83   185.4  854.66   194.6  847.46
   220.8  845.19   242.8  832.35   267.5  811.71   270.3  808.62   273.1  803.71
   287.5  773.73   292.6  768.86  300.41  764.14   309.9  762.98   318.4  764.12
   339.6  767.98   417.7  767.93   429.3   772.6   444.5  784.29   489.7  806.08
   509.8  810.87   535.3  821.93   558.3  826.61   594.8  827.84   634.4  834.13
#Mann= 5 ,-1,0
       0      .1       0  133.72     .06       0  266.17      .1       0
  300.41    .045       0   318.4      .1       0
Bank Sta=300.41,318.4
XS Rating Curve= 0 ,0
Exp/Cntr(USF)=0,0
Exp/Cntr=0.3,0.1

Type RM Length L Ch R = 1 ,5493    ,503.3,500,495.7
XS GIS Cut Line= 6
1633676.48907667393835.9042273461633584.66150442 393855.13483192
1633498.89724025393872.7387993341633425.25992034393887.089492425
1633326.66595742393903.8007450851633074.01948109393946.622509837
#Sta/Elev= 30
       0  807.87    12.6  799.32    16.7  797.72    24.9   796.8    41.3  798.93
    61.7  795.98    86.2  789.56   106.6  789.83     127  788.16   155.6  781.24
   167.9  776.46   192.4  775.05   237.2  759.44     286  758.88   298.1  757.48
  302.83  755.49   310.3  754.45   318.4   755.5   322.5  756.97   330.6  763.93
   350.9  776.45     359  785.14   371.2  794.57   448.2   841.9   468.5  843.42
   476.6  848.84   492.9  857.34     510  863.78   557.8  880.31   612.6  895.45
#Mann= 3 ,-1,0
       0      .1       0  302.83    .045       0   318.4      .1       0
Bank Sta=302.83,318.4
XS Rating Curve= 0 ,0
Exp/Cntr(USF)=0,0
Exp/Cntr=0.3,0.1

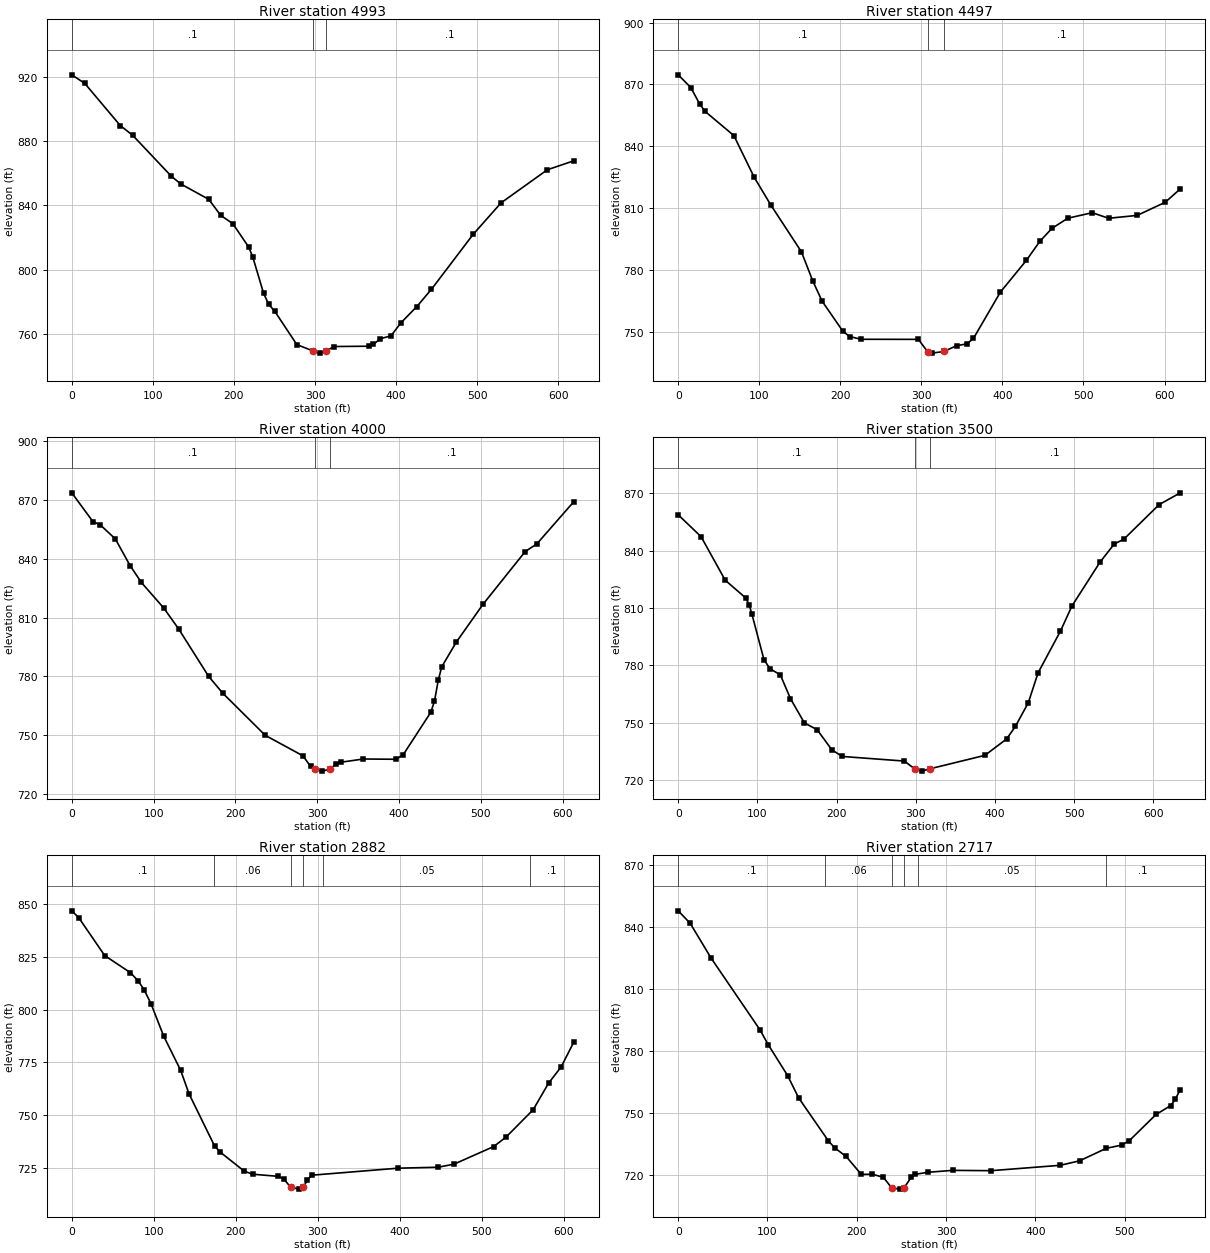
Type RM Length L Ch R = 1 ,4993    ,497,495.9,494.1
XS GIS Cut Line= 6
1633485.10921009393241.9877642541633277.37274893393392.019616425
1633196.30532576393450.5693680941633135.50459434 393494.48135376
1633063.57593243393547.7276383341632986.52753009393609.250481173
#Sta/Elev= 30
       0  921.27      16  915.96    59.8  889.69    75.2  883.57   122.9  858.06
   134.4  853.31     169  843.69   183.8  833.67   198.6   828.6   218.3  813.93
   223.3  807.75   236.6  785.18     243  778.24   250.3  774.04   277.6  753.23
   297.3  749.33   306.2  747.91  314.09749.3497   323.4  752.02   366.4  752.22
   372.1  753.38   380.7  756.91   393.8  758.68   405.8  766.68   425.6   776.9
   443.7  787.71   495.1  821.89   529.5   841.5   586.6  862.13   619.3  867.72
#Mann= 3 ,-1,0
       0      .1       0   297.3    .045       0  314.09      .1       0
Bank Sta=297.3,314.09
XS Rating Curve= 0 ,0
Exp/Cntr(USF)=0,0
Exp/Cntr=0.3,0.1

Type RM Length L Ch R = 1 ,4497    ,493.8,497.1,499.8
XS GIS Cut Line= 6
1633067.16024284392912.589800999 1632882.5687485393091.986423835
1632814.48916025393165.6125889271632764.39444417393222.302108094
1632710.99363235393294.103473678 1632652.2565451393370.896955252
#Sta/Elev= 30
       0  874.68    15.5  868.52    26.6  860.44    33.2  856.92    68.6  845.26
    93.8  824.97   114.4  811.48     152   788.9     166  774.77   177.5     765
     203  750.49   211.4  747.85   225.6  746.51   296.3  746.47   307.7  740.51
   313.3   739.8   327.5  740.59   343.5  743.39   356.2  744.28   364.3  746.95
   397.5  769.37   429.5  784.73   446.1  793.92     461  800.23   480.7  805.19
   510.9  807.86   530.9  805.16   566.2  806.54   600.8  812.89   619.5   819.4
#Mann= 3 ,-1,0
       0      .1       0   307.7    .045       0   327.5      .1       0
Bank Sta=307.7,327.5
XS Rating Curve= 0 ,0
Exp/Cntr(USF)=0,0
Exp/Cntr=0.3,0.1

Type RM Length L Ch R = 1 ,4000    ,498.5,499.9,500.6
XS GIS Cut Line= 6
1632874.74133635392579.6616610881632715.89290075392666.921657175
1632564.22194426392754.2197109161632498.69057925392790.715044752
1632422.09197918 392833.041731761632345.97336501392889.654151335
#Sta/Elev= 30
       0  873.54    25.8  858.91    34.9   857.2    53.2  850.07    71.5  836.33
    85.1  827.87   112.5  814.83   130.8   804.1   167.3  780.03   184.5  771.51
   236.4  750.04   282.6  739.57   291.8  734.19   296.7  732.72   305.6  731.79
  315.77732.7319   322.9  735.48   328.7  736.31   356.4  737.97   396.3  737.83
   405.1  740.17   438.8  761.78   443.3  767.51   447.9  778.05   452.1  784.89
   469.8  797.41   502.7  816.83   554.1   843.6   568.4  847.54   613.6  869.05
#Mann= 3 ,-1,0
       0      .1       0   296.7    .045       0  315.77      .1       0
Bank Sta=296.7,315.77
XS Rating Curve= 0 ,0
Exp/Cntr(USF)=0,0
Exp/Cntr=0.3,0.1

Type RM Length L Ch R = 1 ,3500    ,622.4,618.1,611.8
XS GIS Cut Line= 6
1632634.61287959  392204.99475951632398.97424325392305.711421594
1632306.98230125392344.9219730941632241.17075309 392381.76113826
1632169.66728717392444.7934925111632092.84001301392519.052530333
#Sta/Elev= 30
       0  858.79    28.8  847.39    59.3   824.6    85.4  815.25    89.7   811.5
      93  806.86   108.2  783.12   115.8  778.29   128.9  775.11   141.7  762.66
   159.3  749.94   175.3  746.43   194.1  735.82   207.2  732.41   285.5     730
   298.5  725.92   307.2  724.74  317.51725.9316   387.1  732.98   414.6  741.55
   425.7  748.15   441.9  760.46   454.4  776.21   482.6     798   497.1  811.13
   532.4  833.97   550.5  843.55   562.5  846.01   607.2  864.15   633.9   870.3
#Mann= 3 ,-1,0
       0      .1       0   298.5    .045       0  317.51      .1       0
Bank Sta=298.5,317.51
XS Rating Curve= 0 ,0
Exp/Cntr(USF)=0,0
Exp/Cntr=0.3,0.1

Type RM Length L Ch R = 1 ,2882    ,166.3,164.9,162.2
BEGIN DESCRIPTION:
Structure 2 XS 4
END DESCRIPTION:
XS GIS Cut Line= 6
1632013.77264265391810.200051893 1631953.8761089391882.377729063
1631898.37589182391950.0580398931631850.95735148392008.189157222
 1631788.9591159392086.6532391351631626.12315548392284.436964308
#Sta/Elev= 30
       0  846.61     8.5  843.37    40.2  825.47    71.5  817.42      81  813.51
    88.1  809.44    96.6  802.78   112.1  787.47   132.8   771.3   143.1  760.14
   174.2  735.55   181.3  732.59   210.3  723.68   220.7  722.21   251.6  721.22
   258.6  720.06     267  716.03   277.2  715.17  282.58716.0168   287.4  719.54
   292.8  721.75   398.1  725.06   446.9  725.51   466.3  726.96   514.6  735.26
   529.8  739.75   562.9  752.68   581.6  765.17     597   772.9   612.5  784.64
#Mann= 6 ,-1,0
       0      .1       0  173.79     .06       0     267    .045       0
  282.58     .06       0  306.34     .05       0  558.81      .1       0
Bank Sta=267,282.58
XS Rating Curve= 0 ,0
Exp/Cntr(USF)=0,0
Exp/Cntr=0.3,0.1

Type RM Length L Ch R = 1 ,2717    ,50.3,50.6,49.9
BEGIN DESCRIPTION:
Structure 2 XS 3
END DESCRIPTION:
XS GIS Cut Line= 4
1631868.69064136391755.004020772 1631750.0626071391819.179842586
1631733.53247117391860.0190019231631595.45721818392217.847826585
#Sta/Elev= 30
       0  847.76    13.4  841.71      37  824.75    91.6  790.14   100.7  783.04
   122.6  767.95   134.9  757.21   168.1  736.47   175.2  733.04   188.1  728.84
   205.2  720.13   217.6  720.26   229.9   718.7   239.2  713.62   248.1  713.03
  253.02713.6596   260.9   718.7   265.2  720.16   279.4  721.17   307.3  722.11
   350.6  721.96   427.9  724.56   449.6  726.72   479.6  732.79   496.8  734.35
   505.3  736.46   535.3  749.17   551.7  753.46   556.8  756.49   562.5  761.26
#Mann= 6 ,-1,0
       0      .1       0  164.87     .06       0   239.2    .045       0
  253.02     .06       0  268.93     .05       0  478.93      .1       0
Bank Sta=239.2,253.02
XS Rating Curve= 0 ,0
Exp/Cntr(USF)=0,0
Exp/Cntr=0.3,0.1

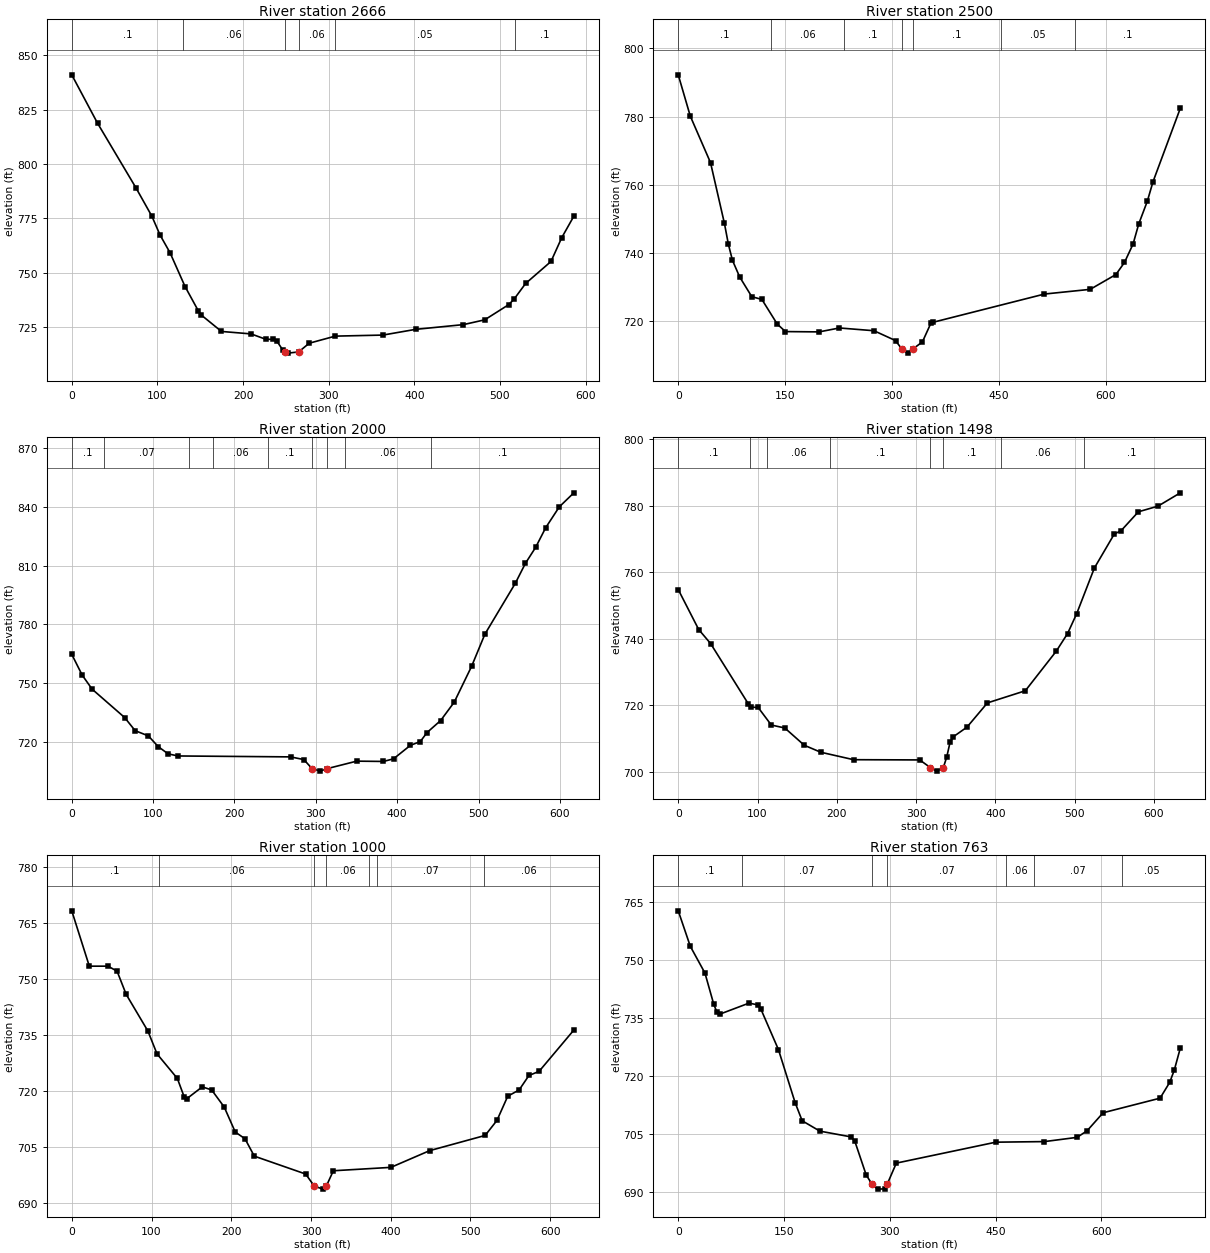
Type RM Length L Ch R = 1 ,2666    ,166,166.4,168
BEGIN DESCRIPTION:
Structure 2 XS 2
END DESCRIPTION:
XS GIS Cut Line= 3
1631832.71328671391719.9990270551631705.33400401391794.870819172
 1631550.7286151 392205.20713441
#Sta/Elev= 30
       0  840.97    30.1  818.72    74.9  789.03    93.5  775.98   103.1  767.29
   114.8  759.11   132.3  743.59   147.8  732.42   151.2  730.51   174.8  722.95
   209.4  721.82   226.5  719.36     235  719.32   239.3  718.61   246.2  714.54
   249.3  713.38   252.4  712.98   264.9  713.53   277.3  717.54   307.7   720.8
   363.3  721.28   401.5  723.91   457.3  726.09   482.2  728.29   510.1  735.24
   516.4  737.76     530  745.02   559.6  755.13   572.2   766.1   586.3  775.97
#Mann= 6 ,-1,0
       0      .1       0     130     .06       0   249.3    .045       0
   264.9     .06       0  307.75     .05       0  517.75      .1       0
Bank Sta=249.3,264.9
XS Rating Curve= 0 ,0
Exp/Cntr(USF)=0,0
Exp/Cntr=0.3,0.1

Type RM Length L Ch R = 1 ,2500    ,495.3,500,508.9
BEGIN DESCRIPTION:
Structure 2 XS 1
END DESCRIPTION:
XS GIS Cut Line= 6
 1631718.2131376391580.6885934171631583.13138676  391717.3697505
1631540.80666825391779.7689039261631457.97710951391933.925419763
1631469.06965667392027.5341416821631478.17656542392194.713367486
#Sta/Elev= 30
       0  792.26    16.9  780.15    45.3  766.49    64.8  748.67    70.4   742.5
    76.1  737.82    86.2  732.96   103.2  727.17   117.3  726.38   138.9  719.14
   150.4  716.94   197.6  716.85   226.1     718   274.6  717.19   304.8   714.3
   313.9  711.76   321.8  710.62  328.89711.7974   342.5  713.91   354.3  719.34
   357.3  719.66   513.7  727.95   577.9  729.33     614  733.68     626  737.23
     638   742.6     646  748.53     658  755.17     666   760.9   704.3  782.45
#Mann= 7 ,-1,0
       0      .1       0  130.42     .06       0  232.18      .1       0
   313.9    .045       0  328.89      .1       0  452.58     .05       0
  556.85      .1       0
Bank Sta=313.9,328.89
XS Rating Curve= 0 ,0
Exp/Cntr(USF)=0,0
Exp/Cntr=0.3,0.1

Type RM Length L Ch R = 1 ,2000    ,497,502.4,506
XS GIS Cut Line= 6
1631660.70997176391321.6067624991631568.47229534391338.377070174
1631310.20607959391385.3333410921631237.01232834391403.277859002
 1631151.4229326391428.4054334161631059.01858984391455.530707255
#Sta/Elev= 30
       0  764.79    12.8  754.23      25  747.08      65  732.63    77.9  725.94
    94.1   723.3   106.3  717.81   118.5  714.12   130.7  713.07   268.9   712.6
   285.2  711.24   295.4   706.6   305.5  705.35   313.7   706.6   350.2  710.43
   383.1  710.28   395.5  711.62   416.1  718.45   428.4  720.42   436.7  725.01
   453.4  731.12   470.1  740.47   491.4  758.67   507.8  775.09   545.1  800.93
   557.6  811.14   570.1  819.23   582.6  829.33   599.3  839.92   617.1  847.02
#Mann= 9 ,-1,0
       0      .1       0      40     .07       0  143.75     .05       0
  173.75     .06       0  241.25      .1       0   295.4    .045       0
   313.7      .1       0  336.25     .06       0  441.61      .1       0
Bank Sta=295.4,313.7
XS Rating Curve= 0 ,0
Exp/Cntr(USF)=0,0
Exp/Cntr=0.3,0.1

Type RM Length L Ch R = 1 ,1498    ,506.5,497.6,488.6
XS GIS Cut Line= 6
1631612.83473942   390986.373181  1631423.057888390931.789628759
 1631346.1548266390912.0724765961631252.14582826390877.649317086
1631101.90465893390815.7196509241631014.44190735 390781.85587351
#Sta/Elev= 30
       0  754.85    25.8  742.83    40.8  738.61    88.3   720.5    92.4  719.47
   100.8  719.37   117.4  714.09   134.4   713.2     159     708   179.7  705.91
   221.2  703.66   304.6  703.59  318.05701.2804   325.9  700.22   334.4  701.29
   338.7  704.49   342.9  708.94   347.2   710.6   364.2  713.45     390  720.75
   437.8   724.4   476.7  736.27   491.1  741.61   502.6   747.6   524.9  761.33
     550  771.55   558.6  772.56   580.4  778.24   605.2  779.95   633.3  783.95
#Mann= 8 ,-1,0
       0      .1       0      90     .07       0  111.86     .06       0
  191.86      .1       0  318.05    .045       0   334.4      .1       0
  406.98     .06       0  511.98      .1       0
Bank Sta=318.05,334.4
XS Rating Curve= 0 ,0
Exp/Cntr(USF)=0,0
Exp/Cntr=0.3,0.1

Type RM Length L Ch R = 1 ,1000    ,236,237.2,235.6
BEGIN DESCRIPTION:
Structure 1 XS 4
END DESCRIPTION:
XS GIS Cut Line= 6
1631487.31760201390296.6462140081631416.94766401390365.966941506
1631310.40260151390489.7996990831631190.85034718390617.597343758
1631118.71138383390670.7406101671631023.10363543 390708.59158434
#Sta/Elev= 30
       0  768.31      22  753.46    45.4  753.46    56.8  752.12    68.2   745.9
    95.5  736.04   106.9  729.92   132.4  723.33   140.9  718.42     144  717.85
   163.6  721.07   175.4  720.25   191.2  715.65     205  708.95   217.2  707.15
   228.9  702.48   293.3  697.68   304.2  694.42   315.2  693.63  319.13694.4105
     328  698.56   400.2  699.47   448.8  703.96   518.4  708.04   533.2  712.08
   546.7  718.56     561  720.25   573.3  724.13     586  725.23   629.6  736.32
#Mann= 7 ,-1,0
       0      .1       0  108.78     .06       0   304.2    .045       0
  319.13     .06       0  372.15      .1       0  382.15     .07       0
  517.15     .06       0
Bank Sta=304.2,319.13
XS Rating Curve= 0 ,0
Exp/Cntr(USF)=0,0
Exp/Cntr=0.3,0.1

Type RM Length L Ch R = 1 ,763     ,90.6,90.6,93
BEGIN DESCRIPTION:
Structure 1 XS 3
END DESCRIPTION:
XS GIS Cut Line= 4
 1631416.5118425 390203.379976131631249.04227104390252.287019122
1630930.40547579390533.8730242291630915.58515973390645.025394666
#Sta/Elev= 30
       0  762.63    17.1  753.48    37.9  746.57    50.4   738.5    54.6  736.61
    58.8  735.97   100.4  738.83   112.9  738.37   117.1  737.31   142.1  726.82
   165.7  713.16   175.7  708.48   200.8  705.81   245.1  704.32   250.4  703.18
   266.5  694.48   274.5   692.2   282.5  690.85   293.1  690.92  296.35 692.166
   309.2  697.56   450.2  702.96   519.2  703.11   565.4   704.2   579.6  705.89
   602.4  710.55   683.1  714.31   696.7  718.36   703.3  721.58   711.8  727.23
#Mann= 7 ,-1,0
       0      .1       0      90     .07       0   274.5    .045       0
  296.35     .07       0  464.46     .06       0  504.46     .07       0
  629.69     .05       0
Bank Sta=274.5,296.35
XS Rating Curve= 0 ,0
Exp/Cntr(USF)=0,0
Exp/Cntr=0.3,0.1

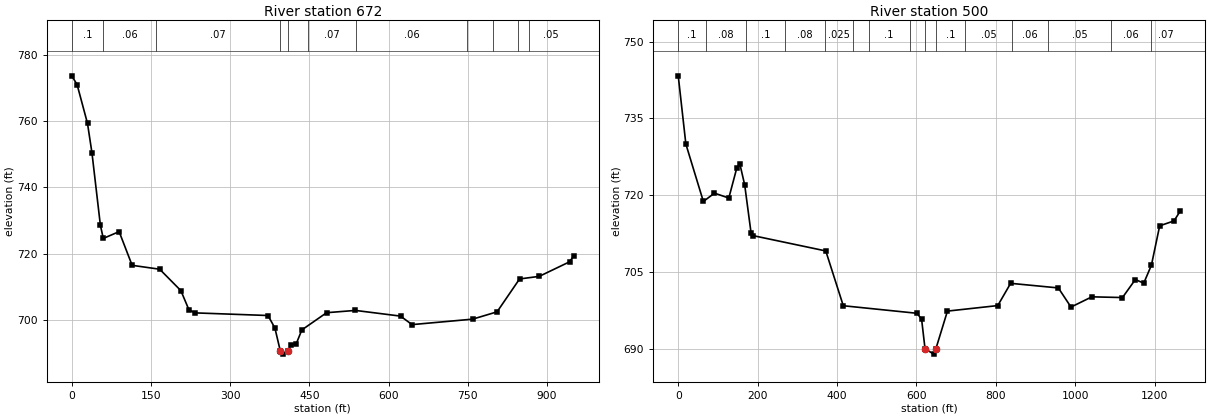
Type RM Length L Ch R = 1 ,672     ,172.8,172.2,171.3
BEGIN DESCRIPTION:
Structure 1 XS 2
END DESCRIPTION:
XS GIS Cut Line= 4
1631486.16732797390126.3143326271631278.68290316390111.494016569
 1630831.1093582390507.1964553241630860.74999031390649.471489484
#Sta/Elev= 30
       0  773.74    10.1  771.08    29.8  759.34    38.2  750.49    54.2  728.56
    59.7   724.6    89.7  726.65   114.3  716.47   166.5  715.29   206.6  708.82
   221.7  703.09   232.8   702.1   371.6   701.3   384.7  697.51   394.8  690.66
   400.4  689.63  409.64690.7098   414.9  692.48     425  692.73   435.7  696.95
   482.6  702.15   537.1  702.84   622.6  701.12   644.4  698.55   759.1   700.2
   805.4  702.41     848  712.35   885.2  713.13   942.7  717.53   950.8  719.37
#Mann= 11 ,-1,0
       0      .1       0      60     .06       0     160     .07       0
   394.8    .045       0  409.64     .05       0  448.01     .07       0
  538.01     .06       0  748.01     .07       0  798.01     .06       0
  845.43     .07       0  865.43     .05       0
Bank Sta=394.8,409.64
XS Rating Curve= 0 ,0
Exp/Cntr(USF)=0,0
Exp/Cntr=0.3,0.1

Type RM Length L Ch R = 1 ,500     ,,,
BEGIN DESCRIPTION:
Structure 1 XS 1
END DESCRIPTION:
XS GIS Cut Line= 6
1631595.32179736389981.2273044181631175.53180826389959.294198424
1630987.74543843390142.7131229191630947.24551943390209.640810594
 1630767.0667802390423.6298270881630804.35345084390644.267237432
#Sta/Elev= 30
       0  743.31    19.2  729.98    63.3  718.75    91.3  720.38   127.4  719.42
   147.4  725.26   155.4  726.02   167.4     722   183.5  712.58   187.5  712.09
   371.7  709.08   415.8  698.37   601.9  696.89   613.2  695.68   621.7  689.99
   643.2  688.91  649.17689.9714   678.2  697.32     805   698.4   837.4  702.75
   957.6  701.85   989.5  698.11  1042.1  700.11  1119.2  699.97  1151.6  703.49
  1172.8  702.78  1192.1   706.3  1212.9  713.99    1249  714.95  1264.9  716.89
#Mann= 15 ,-1,0
       0      .1       0      70     .08       0     170      .1       0
     270     .08       0     370    .025       0  440.36     .05       0
  480.36      .1       0  582.86     .06       0   621.7    .045       0
  649.17      .1       0  722.86     .05       0  841.09     .06       0
  931.09     .05       0 1091.18     .06       0 1191.18     .07       0
Bank Sta=621.7,649.17
XS Rating Curve= 0 ,0
Exp/Cntr(USF)=0,0
Exp/Cntr=0.3,0.1
LCMann Table=0

Chan Stop Cuts=-1
Use User Specified Reach Order=0
Composite Channel Slope=5